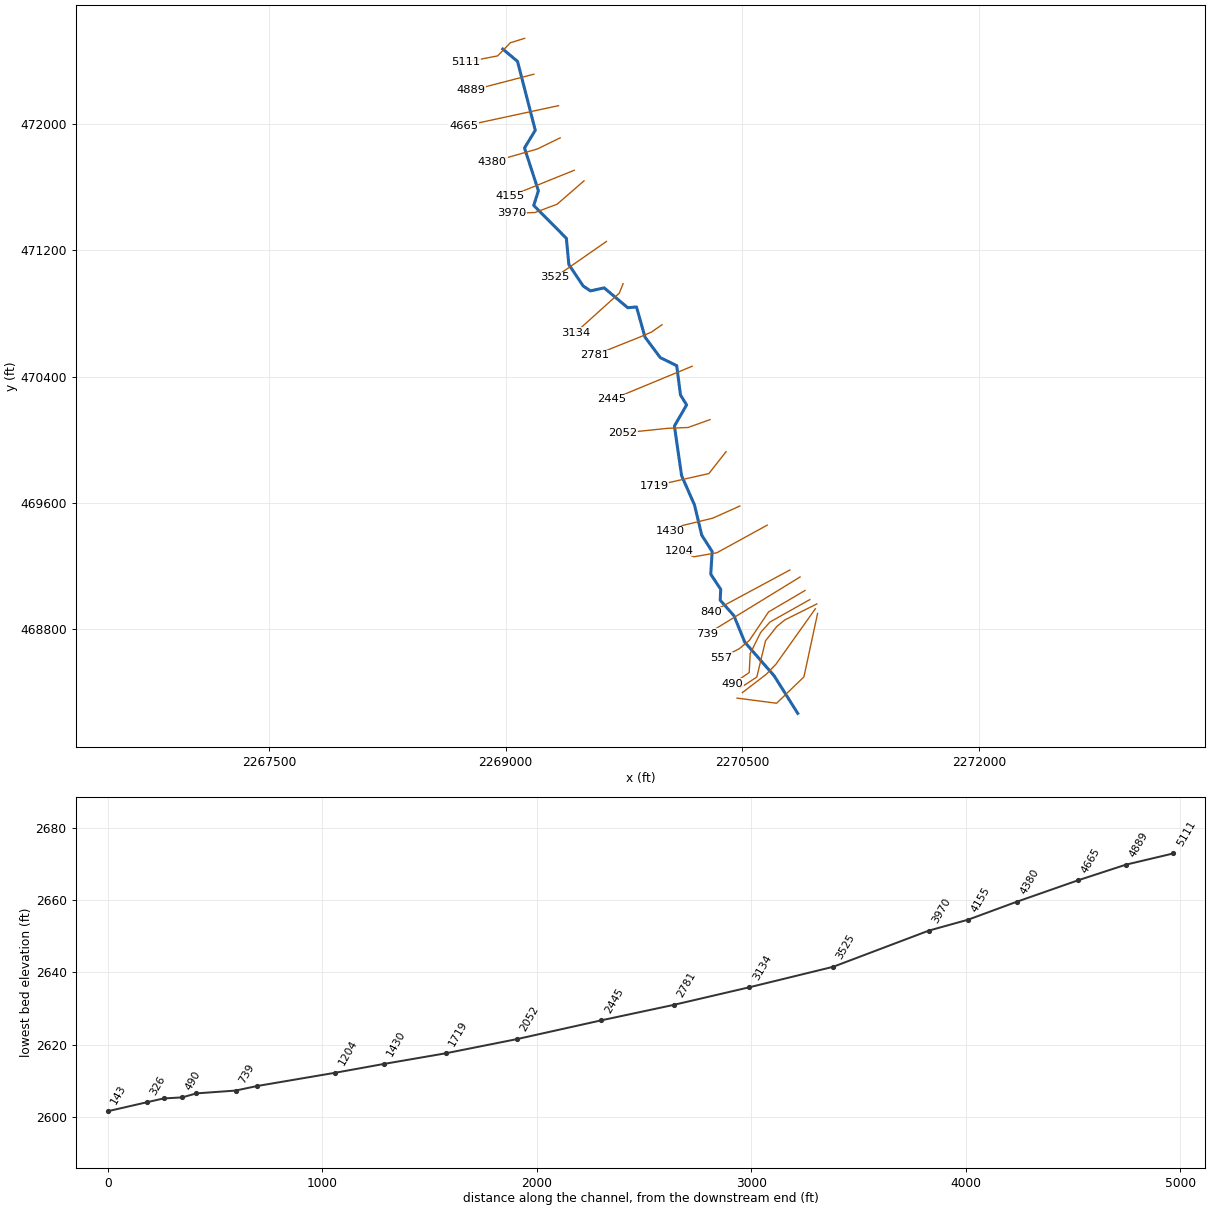
--- LTLTHRNYCK.prj (project) ---

Proj Title=LTLTHRNYCK
Current Plan=p01
Default Exp/Contr=0,0
English Units
Geom File=g01
Flow File=f01
Plan File=p01
Background Map Layer=Inundation Boundary (01pct Value_0)
BEGIN DESCRIPTION:
----------MODEL BY WOOD PLC 2021----------
Stream Name: Little Thorny Creek
Flood Zone: Enhanced Approximate
Pocahontas County, WV
HEC-RAS Version: RAS 6.1
Vertical Datum: NAVD88
Projection: NAD 1983 StatePlane West Virginia S FIPS 4702 (US Feet)
Terrain: 1-meter LIDAR (FEMA Region III 3DEP collected 2016-2018)
Land Use: 2019 NLCD
Hydrologic Method:
WV SIR2010-5033 regression equations
Model Notes:
Tie in with Thorny Creek
END DESCRIPTION:
DSS File=dss
DSS Export Rating Curves= 0
DSS Export Rating Curve Sorted= 0
DSS Export Volume Flow Curves= 0
DXF OffsetX= 0
DXF OffsetY= 0
DXF ScaleX= 0
DXF ScaleY= 0

--- LTLTHRNYCK.p01 (plan) ---

Plan Title=Floodplain
Program Version=6.10
Short Identifier=Floodplain
Geom File=g01
Flow File=f01
Subcritical Flow
K Sum by GR= 0
Std Step Tol= 0.01
Critical Tol= 0.01
Num of Std Step Trials= 20
Max Error Tol= 0.3
Flow Tol Ratio= 0.001
Split Flow NTrial= 30
Split Flow Tol= 0.02
Split Flow Ratio= 0.02
Log Output Level= 0
Friction Slope Method= 1
Unsteady Friction Slope Method= 2
Unsteady Bridges Friction Slope Method= 1
Parabolic Critical Depth
Global Vel Dist= 0 , 0 , 0
Global Log Level= 0
CheckData=True
Encroach Param=-1 ,0,0, 0
Computation Interval=0.1SEC
Output Interval=1SEC
Instantaneous Interval=Max Profile
Mapping Interval=1HOUR
Computation Time Step Use Courant=        0
Computation Time Step Use Time Series=    0
Computation Time Step Count To Double=0
Computation Time Step Max Doubling=0
Computation Time Step Max Halving=0
Computation Time Step Residence Courant=0
Run HTab= 0
Run UNet= 0
Run Sediment= 0
Run PostProcess= 0
Run WQNet= 0
Run RASMapper=-1
UNET Theta= 0
UNET Theta Warmup= 0
UNET ZTol= 0
UNET ZSATol= 0
UNET MxIter= 0
UNET Max Iter WO Improvement= 0
UNET MaxInSteps= 0
UNET DtIC= 0
UNET DtMin= 0
UNET MaxCRTS= 0
UNET WFStab= 0
UNET SFStab= 0
UNET WFX= 1
UNET SFX= 1
UNET Gravity=32.174
UNET 1D Methodology=Finite Difference
UNET DSS MLevel= 1
UNET Pardiso=0
UNET DZMax Abort= 0
UNET Use Existing IB Tables= 0
UNET Froude Reduction=False
UNET Froude Limit= 0
UNET Froude Power= 0
UNET D1 Cores= 0
UNET WindReference=Eulerian
UNET WindDragFormulation=Hsu (1988)
UNET D2 Coriolis=0
UNET D2 Cores= 0
UNET D2 Theta= 1
UNET D2 Theta Warmup= 1
UNET D2 Z Tol= 0.01
UNET D2 Volume Tol= 0.01
UNET D2 Max Iterations= 20
UNET D2 Equation= 0
UNET D2 RampUpFraction=0.1
UNET D2 TimeSlices= 1
UNET D2 Turbulence Formulation=Non-Conservative (original)
UNET D2 Eddy Viscosity=0.3
UNET D2 Transverse Eddy Viscosity=0.1
UNET D2 Smagorinsky Mixing=0
UNET D2 BCVolumeCheck=0
UNET D2 Cores=0
UNET D2 SolverType=PARDISO (Direct)
UNET D2 Minimum Iterations= 2147483647
UNET D2 Maximum Iterations= 2147483647
UNET D2 Restart Number= 10
UNET D2 Relaxation Coeff=1.3
UNET D2 SOR Precondition Iterations= 10
UNET D2 ILUT Maximum Fill= 8
UNET D2 ILUT Tolerance=1E-08
UNET D1D2 MaxIter= 0
UNET D1D2 ZTol=0.01
UNET D1D2 QTol=0.1
UNET D1D2 MinQTol=1
DSS File=dss
Write IC File= 0
Write IC File at Fixed DateTime=0
Write IC File at Sim End=0
Echo Input=False
Echo Parameters=False
Echo Output=False
Write Detailed= 0
HDF Write Warmup=0
HDF Write Time Slices=0
HDF Flush=0
HDF Compression= 1
HDF Chunk Size= 1
HDF Spatial Parts= 1
HDF Use Max Rows=0
HDF Fixed Rows= 1
Calibration Method= 0
Calibration Iterations= 20
Calibration Max Change=0.05
Calibration Tolerance=0.2
Calibration Maximum=1.5
Calibration Minimum=0.5
Calibration Optimization Method= 1
WQ AD Non Conservative
WQ ULTIMATE=-1
WQ Max Comp Step=1HOUR
WQ Output Interval=15MIN
WQ Output Selected Increments= 0
WQ Output face flow=0
WQ Output face velocity=0
WQ Output face area=0
WQ Output face dispersion=0
WQ Output cell volume=0
WQ Output cell surface area=0
WQ Output cell continuity=0
WQ Output cumulative cell continuity=0
WQ Output face conc=0
WQ Output face dconc_dx=0
WQ Output face courant=0
WQ Output face peclet=0
WQ Output face adv mass=0
WQ Output face disp mass=0
WQ Output cell mass=0
WQ Output cell source sink temp=0
WQ Output nsm pathways=0
WQ Output nsm derived pathways=0
WQ Create Restart=0
WQ Fixed Restart=0
WQ System Summary=0
WQ Write To DSS=0
Sorting and Armoring Iterations= 10
XS Update Threshold= 0.02
Bed Roughness Predictor= 0
Hydraulics Update Threshold= 0.02
Energy Slope Method= 1
Volume Change Method= 1
Sediment Retention Method= 0
Sediment TS Multiplier= 1
Warm Up Method= 0
XS Weighting Method= 0
Number of US Weighted Cross Sections= 1
Number of DS Weighted Cross Sections= 1
Upstream XS Weight=0
Main XS Weight=1
Downstream XS Weight=0
Number of DS XS's Weighted with US Boundary= 1
Upstream Boundary Weight= 1
Weight of XSs Associated with US Boundary= 0
Number of US XS's Weighted with DS Boundary= 1
Downstream Boundary Weight= 0.5
Weight of XSs Associated with DS Boundary= 0.5
Percentile Method= 0
Sediment Output Level= 3
Mass or Volume Output= 0
Output Increment Type= 1
Profile and TS Output Increment= 1
Transport Output Increment 1
XS Output Flag= 0
XS Output Increment= 10
Read HDF5 Sediment Hotstart= 0
Sediment Hotstart Type= 0
Write Gradation File= 0
Read Gradation Hotstart= 0
Write HDF5 File= 1
Write Binary Output= 1
Write DSS Sediment File= 0
DSS Sediment Output Type= 1
SV Curve= 0
Specific Gage Flag= 0
Subcell Erosion Methods= 0
Subcell Deposition Methods= 0
Advection Scheme= 1
Matrix Solver= 0
Implicit Weighting Factor= 1
Maximum Outer Loop Convergence Iterations= 5
Convergence Maximum Absolute= 0.001
Convergence RMSE= 0.0001
Grain Fractions Max Abs Error= 0.001
Max Subgrid Regions= 1
Max Subgrid Length Scale= 3.402823E+38
Initial Layer Thickness= 3.402823E+38
Min Layer Thickness= 3.402823E+38
Max Layer Thickness= 3.402823E+38
Number of Layers= 5

--- LTLTHRNYCK.f01 (steady flow) ---

Flow Title=Flow
Program Version=6.10
Number of Profiles= 6
Profile Names=01pct,10pct,04pct,02pct,0_2pct,01plus
River Rch & RM=LTLTHRNYCK,Main,5111
     631     335     444     535     880     934
Boundary for River Rch & Prof#=LTLTHRNYCK,Main            , 1
Up Type= 0
Dn Type= 3
Dn Slope=0.01889
Boundary for River Rch & Prof#=LTLTHRNYCK,Main            , 2
Up Type= 0
Dn Type= 3
Dn Slope=0.01889
Boundary for River Rch & Prof#=LTLTHRNYCK,Main            , 3
Up Type= 0
Dn Type= 3
Dn Slope=0.01889
Boundary for River Rch & Prof#=LTLTHRNYCK,Main            , 4
Up Type= 0
Dn Type= 3
Dn Slope=0.01889
Boundary for River Rch & Prof#=LTLTHRNYCK,Main            , 5
Up Type= 0
Dn Type= 3
Dn Slope=0.01889
Boundary for River Rch & Prof#=LTLTHRNYCK,Main            , 6
Up Type= 0
Dn Type= 3
Dn Slope=0.01889
DSS Import GetInterval= 0
DSS Import GetPeak= 0
DSS Import FillOption= 0

--- LTLTHRNYCK.g01 (geometry) ---

Geom Title=Geometry
Program Version=6.10

River Reach=LTLTHRNYCK      ,Main
Reach XY= 30
     2268982.403      472476.3612269075.81075439472397.645569069
2269188.25486483471961.7393714982269119.95373422471849.364681146
2269208.05315253  471578.2408543 2269178.4090868471485.313505735
2269385.09088541471277.3790901642269400.93072104471110.668475071
     2269491.589      470974.8362269537.90438576470944.007788374
     2269624.573      470963.1222269773.89742126470837.472715818
2269829.51361434470842.1700294222269883.29443342470651.183739454
2269979.91379533470521.4570437462270084.30324578470470.106893362
2270108.17294573470284.6204017942270147.06377249470221.687973046
2270069.63567195 470087.69139723     2270115.296      469773.403
     2270197.151      469587.344 2270242.7372312469396.458428672
2270308.96015371469292.769563826     2270299.952      469148.912
2270363.04543762469053.590140228     2270359.856      468984.451
2270446.83749163468886.0060322152270515.53295756468718.340836288
     2270702.116      468504.6292270851.08991734468267.224493497

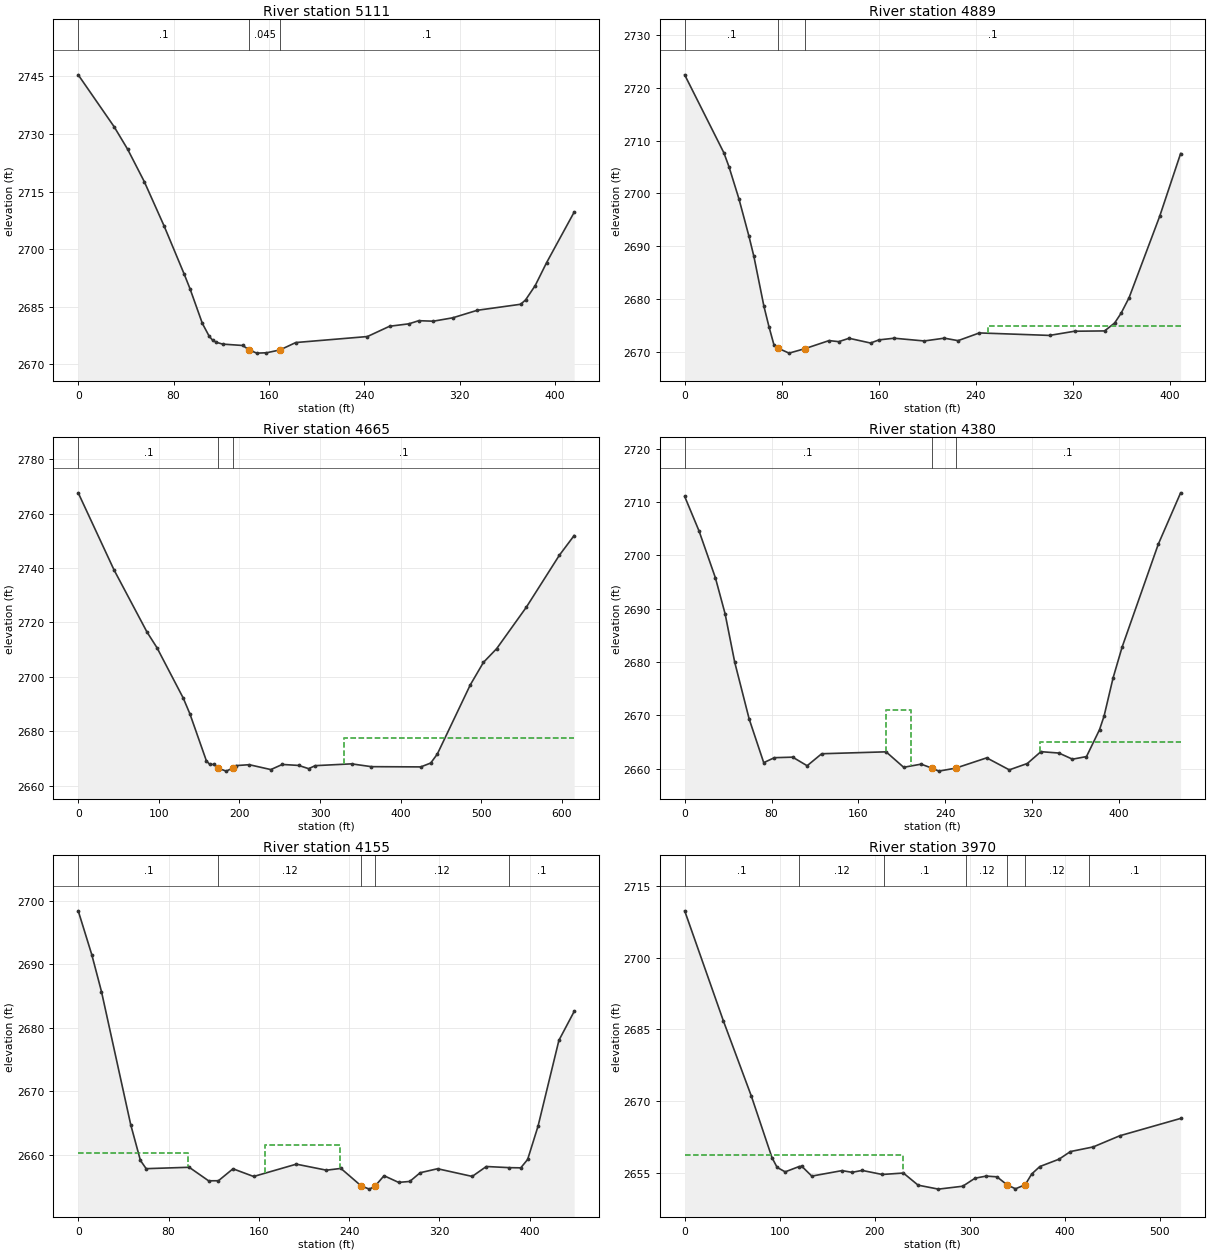
Type RM Length L Ch R = 1 ,5111    ,444.3,221.8,444.3
XS GIS Cut Line= 4
2269121.06768909472544.1212076542269030.11074636472516.047470398
2268949.80199821472432.8741997052268748.07320716472394.110272346
#Sta/Elev= 30
       0 2745.43    30.2 2731.88    41.5 2726.03    55.4 2717.64    72.1 2706.05
    88.8 2693.62    93.8 2689.72   104.2 2680.66   109.9 2677.34   112.7 2676.33
   115.9 2675.75   121.2 2675.28   138.1 2674.92143.30322673.794   149.8 2672.93
     158 2673.02169.3025 2673.76   182.6 2675.69   242.7 2677.25   261.3 2679.93
   277.6 2680.57   285.8 2681.38     298 2681.25   314.3 2682.13   334.9 2684.09
   371.3 2685.66   375.4 2686.78   383.5 2690.52     393 2696.46   416.2 2709.66
#Mann= 3 ,-1,0
       0      .1       0143.3032    .045       0169.3025      .1       0
Bank Sta=143.3032,169.3025
XS Rating Curve= 0 ,0
Exp/Cntr=0.3,0.1

Type RM Length L Ch R = 1 ,4889    ,225.3,224.6,224.2
XS GIS Cut Line= 2
2269179.46405361472316.8470154672268783.53623935472213.977553152
#Sta/Elev= 30
       0 2722.44    32.3 2707.71    36.5 2705.09    44.7 2699.03      53 2691.93
    57.1 2688.09    65.4 2678.64    69.5 2674.84    73.7 2671.32    76.92670.754
    86.1 2669.81    99.22670.655   119.1 2672.18   127.1 2671.98   135.6 2672.62
   153.3 2671.72   160.4 2672.32   172.8 2672.63   197.6 2672.11   214.2 2672.64
   225.5 2672.17   243.1 2673.63     301 2673.16   321.6 2673.95   346.4 2674.01
   354.7 2675.51     360 2677.36   366.6  2680.3   391.9 2695.73   409.1 2707.56
#Mann= 3 ,-1,0
       0      .1       0    76.9    .045       0    99.2      .1       0
#XS Ineff= 2 , 0
                             250            2675
Permanent Ineff=
       F       F
Bank Sta=76.9,99.2
XS Rating Curve= 0 ,0
Exp/Cntr(USF)=0,0
Exp/Cntr=0.3,0.1

Type RM Length L Ch R = 1 ,4665    ,285.4,284.3,285.8
XS GIS Cut Line= 2
 2269335.5648876472117.590777686 2268734.2703547471988.217047461
#Sta/Elev= 30
       0 2767.59    44.4 2739.31    85.3  2716.5    97.6 2710.79   130.3 2692.24
   138.5 2686.49   158.9 2669.29     163 2667.94   168.2 2667.89  173.88 2666.51
   183.5 2665.45   191.7 2666.56   195.8 2667.48   212.1 2667.81   238.9 2666.02
   253.1  2667.9   273.5 2667.54   285.8 2666.35     294 2667.46     339 2668.12
   363.5 2667.09   424.9    2667   437.2 2668.42   445.4 2671.72   486.3 2697.12
   502.6 2705.37     519  2710.4   555.8 2725.62   596.7 2744.66   615.1 2751.92
#Mann= 3 ,0,0
       0      .1       0  173.88    .045       0   191.7      .1       0
#XS Ineff= 2 , 0
                             330         2677.69
Permanent Ineff=
       F       F
Bank Sta=173.88,191.7
XS Rating Curve= 0 ,0
Exp/Cntr=0.3,0.1

Type RM Length L Ch R = 1 ,4380    ,223.9,225.6,226.6
XS GIS Cut Line= 3
2269345.59568074471913.3402396082269200.69942063471842.753959886
2268916.38266856471761.807009701
#Sta/Elev= 30
       0 2711.06    13.2  2704.6    28.3  2695.8    37.2 2689.08    46.1 2679.96
    59.4 2669.32    72.8 2661.13    82.6 2662.06    99.5 2662.16   112.8 2660.55
   126.2  2662.8   185.5 2663.16   201.7 2660.26   217.8 2660.85   227.6 2660.11
   234.1 2659.54   249.6  2660.1   278.2 2662.03     299 2659.78   315.6 2660.97
   328.1 2663.19   344.7 2662.93   357.2 2661.78   370.1 2662.27   382.1 2667.31
   386.3 2669.87   394.6 2677.03   402.9  2682.8   436.2 2702.09   456.8 2711.74
#Mann= 3 ,-1,0
       0      .1       0   227.6    .045       0   249.6      .1       0
#XS Ineff= 2 ,-1
  185.22  208.47    2671  327.61   456.8 2665.07
Permanent Ineff=
       F       F
Bank Sta=227.6,249.6
XS Rating Curve= 0 ,0
Exp/Cntr(USF)=0,0
Exp/Cntr=0.3,0.1

Type RM Length L Ch R = 1 ,4155    ,182,184.4,181.9
XS GIS Cut Line= 2
  2269435.266914 471708.466249932269028.04379355471543.658605894
#Sta/Elev= 30
       0  2698.4      12 2691.51    20.6  2685.7    46.5 2664.75    55.1 2659.12
    60.2 2657.82    98.3 2658.04   115.5 2655.91   124.2 2655.92   137.1  2657.8
   155.4 2656.59   193.2 2658.53   219.9 2657.58   232.7 2657.86   250.7  2655.1
   257.9  2654.6   262.9 2655.07   270.9 2656.71   283.8 2655.66   293.7 2655.81
   302.9 2657.18   318.3 2657.81     349  2656.6   361.5 2658.16   381.9 2657.98
     392 2657.95   398.1 2659.27   407.3  2664.5   425.8 2678.02   439.3 2682.56
#Mann= 5 ,-1,0
       0      .1       0   124.2     .12       0   250.7    .045       0
   262.9     .12       0   381.9      .1       0
#XS Ineff= 2 ,-1
       0   97.442660.244  165.32  231.492661.513
Permanent Ineff=
       F       F
Bank Sta=250.7,262.9
XS Rating Curve= 0 ,0
Exp/Cntr(USF)=0,0
Exp/Cntr=0.3,0.1

Type RM Length L Ch R = 1 ,3970    ,439.9,445.5,447
XS GIS Cut Line= 4
2269497.25772954471641.4105345232269326.31197153471493.063087138
2269186.07527315471440.5935741392269040.24883671471434.887844088
#Sta/Elev= 30
       0 2709.85    40.6 2686.87    70.3 2670.97    91.9 2658.15    97.3  2656.1
   105.8 2655.17     120 2656.25   123.2 2656.35   133.8 2654.28   165.6 2655.43
   176.2 2655.07   186.8 2655.47   207.9 2654.62   230.2 2654.92   245.7 2652.38
   267.1 2651.55   292.7 2652.16   305.6 2653.84   317.3 2654.28   328.7 2654.13
   339.4 2652.44   348.2 2651.62   358.4 2652.47   365.3 2654.73   373.8 2656.28
     394 2657.82     406 2659.42     430 2660.39     458 2662.73     522 2666.36
#Mann= 7 ,-1,0
       0      .1       0     120     .12       0     210      .1       0
  296.34     .12       0   339.4    .045       0   358.4     .12       0
  426.07      .1       0
#XS Ineff= 2 , 0
          230.23 2658.63
Permanent Ineff=
       F       F
Bank Sta=339.4,358.4
XS Rating Curve= 0 ,0
Exp/Cntr(USF)=0,0
Exp/Cntr=0.3,0.1

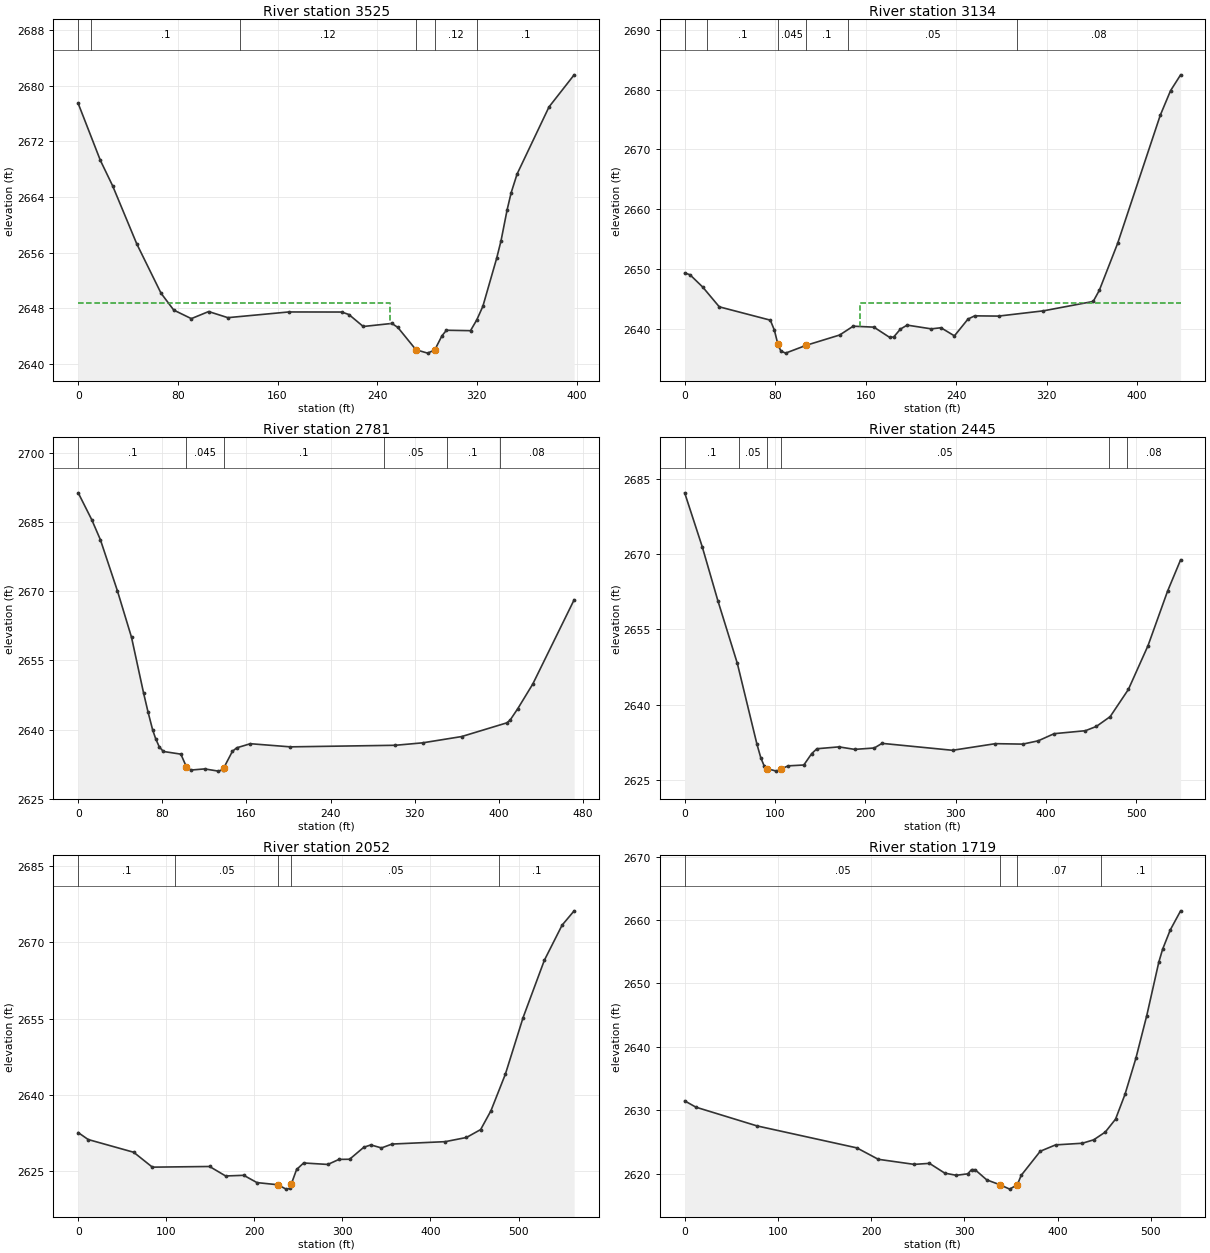
Type RM Length L Ch R = 1 ,3525    ,387.1,390.4,386.6
XS GIS Cut Line= 2
2269638.79536527471256.990624566 2269311.9998678471029.633795356
#Sta/Elev= 30
       0 2677.44    17.8 2669.25    27.6 2665.61      47 2657.25    66.5 2650.15
    76.7 2647.73    90.8  2646.5   104.7 2647.52   120.1 2646.64   168.9 2647.46
   211.5 2647.45   217.3 2647.09   228.8 2645.37   251.8 2645.81   256.6 2645.23
 271.1342642.022   280.5 2641.54   286.2    2642     292 2644.04   295.6 2644.83
   314.9 2644.77   319.9 2646.31   324.8 2648.26   335.9 2655.18   339.4  2657.7
   344.3 2662.15   347.5 2664.59   352.3  2667.3   377.9 2676.94   398.1 2681.56
#Mann= 6 ,-1,0
       0     .12       0      10      .1       0     130     .12       0
 271.134    .045       0   286.2     .12       0     320      .1       0
#XS Ineff= 2 , 0
          250.37 2648.73
Permanent Ineff=
       F       F
Bank Sta=271.134,286.2
XS Rating Curve= 0 ,0
Exp/Cntr(USF)=0,0
Exp/Cntr=0.3,0.1

Type RM Length L Ch R = 1 ,3134    ,357,353.6,334.5
XS GIS Cut Line= 3
2269744.55776929470989.559952258 2269720.7283083470929.965170899
2269442.84228448470679.247367386
#Sta/Elev= 30
       0  2649.3     4.7    2649      16 2646.93    30.6 2643.63    75.7  2641.4
    79.3 2639.7482.394172637.373      85 2636.25    89.2 2635.88 107.5942637.199
     137 2638.91     149 2640.39   167.3 2640.23   181.2 2638.52   184.8 2638.58
   190.8 2639.91   196.7 2640.57   218.1 2639.94   226.6 2640.13   238.5 2638.77
   250.5 2641.58   256.4 2642.12   277.5 2642.08   317.2 2642.96   361.2 2644.53
   366.6 2646.39   382.8 2654.25   420.5  2675.7   429.6 2679.82   438.5 2682.47
#Mann= 6 ,-1,0
       0     .12       0      20      .1       082.39417    .045       0
 107.594      .1       0  144.18     .05       0  294.18     .08       0
#XS Ineff= 2 , 0
                          155.32         2644.34
Permanent Ineff=
       F       F
Bank Sta=82.39417,107.594
XS Rating Curve= 0 ,0
Exp/Cntr(USF)=0,0
Exp/Cntr=0.3,0.1

Type RM Length L Ch R = 1 ,2781    ,317.7,336.1,321.1
XS GIS Cut Line= 4
 2269990.7280043470729.2090093822269924.46441971 470683.12460467
2269851.00710151470651.6428968712269562.40406767470535.806651587
#Sta/Elev= 30
       0 2691.29    12.9 2685.45    21.1 2681.12    37.2 2670.11    50.7 2659.98
    62.2 2647.87    66.4  2643.8    70.8 2639.91    73.7 2637.99    77.1 2636.24
      81 2635.25    97.6 2634.67   102.8 2631.97   107.1 2631.22   120.2 2631.47
   133.3 2630.99   137.6 2631.32   138.5 2631.73   146.6 2635.27   150.7 2636.04
   163.7 2636.93   201.6 2636.25   301.6 2636.59   327.5 2637.12   364.6 2638.48
   407.7 2641.46   410.8 2642.08     418 2644.53   432.3 2649.88   471.6 2668.12
#Mann= 6 ,-1,0
       0      .1       0   102.8    .045       0   138.5      .1       0
  290.63     .05       0  350.63      .1       0  400.63     .08       0
Bank Sta=102.8,138.5
XS Rating Curve= 0 ,0
Exp/Cntr(USF)=0,0
Exp/Cntr=0.3,0.1

Type RM Length L Ch R = 1 ,2445    ,395.3,392.8,381.7
XS GIS Cut Line= 2
2270182.08320405470466.5530270792269674.76632972470256.647470559
#Sta/Elev= 30
       0 2682.16    19.4 2671.44    36.7  2660.7    58.3 2648.18      80 2632.09
    84.3 2629.37    88.2 2627.68    91.3 2627.22   101.6 2626.73   106.6 2627.16
   114.6 2627.78   131.9 2627.95   140.6 2630.22   146.4 2631.19   170.8 2631.56
   188.2 2631.06   209.9 2631.34   218.5 2632.26   296.5 2630.88     344  2632.2
   374.3 2632.11   391.4 2632.77     409 2634.19   443.6 2634.78   455.7 2635.63
     471 2637.58   491.2 2643.01   512.9 2651.72   534.5 2662.55     549 2668.82
#Mann= 6 ,-1,0
       0      .1       0      60     .05       0    91.3    .045       0
   106.6     .05       0     470      .1       0     490     .08       0
Bank Sta=91.3,106.6
XS Rating Curve= 0 ,0
Exp/Cntr(USF)=0,0
Exp/Cntr=0.3,0.1

Type RM Length L Ch R = 1 ,2052    ,330.5,333,335.2
XS GIS Cut Line= 4
2270295.46958618470128.327009807 2270155.8241971470078.500207383
2270025.84420522470073.1196198582269742.52971162470043.819890296
#Sta/Elev= 30
       0 2632.63    11.3 2631.27      63 2628.77    84.2 2625.85   149.2 2625.98
   167.4 2624.12     188 2624.25     203 2622.82226.82862622.396     236 2621.54
     240 2621.67242.04812622.569     248 2625.39     256 2626.67   283.5 2626.38
   296.1 2627.37   308.2  2627.4   324.3 2629.75   332.3 2630.21   344.4 2629.62
   356.4 2630.38   416.8 2630.85   440.9 2631.67     457 2633.22   468.7 2636.91
   485.1 2644.09   505.2 2655.18   529.4 2666.44   549.5 2673.31   563.2 2676.12
#Mann= 5 ,-1,0
       0      .1       0     110     .05       0226.8286    .045       0
242.0481     .05       0  478.36      .1       0
Bank Sta=226.8286,242.0481
XS Rating Curve= 0 ,0
Exp/Cntr(USF)=0,0
Exp/Cntr=0.3,0.1

Type RM Length L Ch R = 1 ,1719    ,288.8,289.1,290.1
XS GIS Cut Line= 3
 2270397.0031505469925.3564275272270287.90204328469786.435560777
2269941.40967669469708.611823967
#Sta/Elev= 30
       0 2631.51    12.1 2630.51    77.6 2627.56   184.6  2624.1   207.6  2622.3
   246.1  2621.5   262.5 2621.66   278.9 2620.12   291.2 2619.78   303.5 2620.01
   307.6 2620.67   311.4 2620.66   323.9 2619.06338.21262618.279   348.5  2617.6
356.71262618.295   360.8 2619.76   381.3 2623.57   397.7 2624.57   426.4 2624.83
   438.6 2625.37     451 2626.59     462 2628.62   472.1 2632.51   483.8  2638.2
   495.5 2644.95   508.4 2653.36   512.5  2655.4   520.7 2658.44   531.8 2661.45
#Mann= 4 ,-1,0
       0     .05       0338.2126    .045       0356.7126     .07       0
  446.64      .1       0
Bank Sta=338.2126,356.7126
XS Rating Curve= 0 ,0
Exp/Cntr(USF)=0,0
Exp/Cntr=0.3,0.1

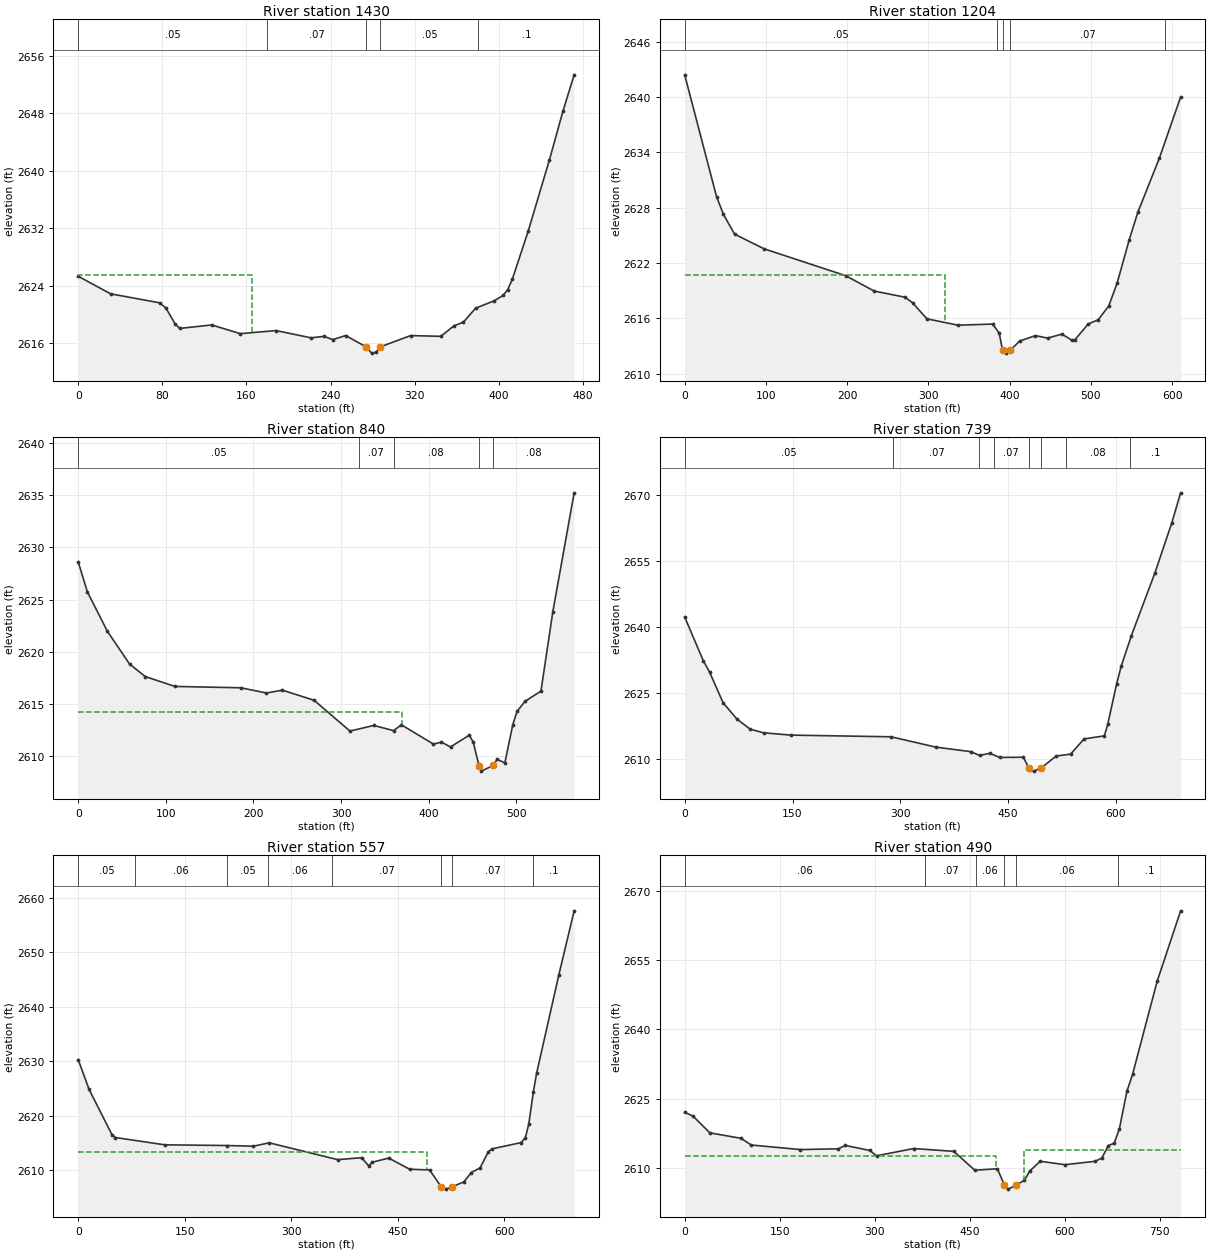
Type RM Length L Ch R = 1 ,1430    ,223,225.4,221.8
XS GIS Cut Line= 4
2270484.25857918469580.8968847142270312.62318989   469503.908171
2270125.44879416469458.7037886352270042.80953265469420.562591015
#Sta/Elev= 30
       0 2625.34    30.8 2622.89    77.5 2621.64    83.4 2620.92    92.2  2618.7
    96.5 2618.08     127 2618.56   154.2 2617.35   188.1 2617.78   221.5 2616.77
   233.8 2616.97   242.1 2616.52   254.4 2617.09   273.6 2615.53   279.1 2614.64
   283.2 2614.75   287.3 2615.51   316.1 2617.08   344.9 2616.98   357.3 2618.43
   366.4 2618.95   377.9 2620.89   395.3  2621.9   404.1 2622.66   408.5 2623.48
   412.9 2624.93     428 2631.62   448.2 2641.54   461.1 2648.34   471.7 2653.37
#Mann= 5 ,-1,0
       0     .05       0     180     .07       0   273.6    .045       0
   287.3     .05       0  380.67      .1       0
#XS Ineff= 2 , 0
          165.28 2625.49
Permanent Ineff=
       F       F
Bank Sta=273.6,287.3
XS Rating Curve= 0 ,0
Exp/Cntr(USF)=0,0
Exp/Cntr=0.3,0.1

Type RM Length L Ch R = 1 ,1204    ,353.3,363.8,361.1
XS GIS Cut Line= 4
2270658.00630241469460.0430955252270338.28861484469284.600755607
2270193.82878368469259.5003811252270102.20223264469297.303609816
#Sta/Elev= 30
       0 2642.39    39.2 2629.19    47.7 2627.26    61.4 2625.12    97.7 2623.53
   198.3 2620.61   233.2 2618.95   271.3 2618.28   280.4 2617.69   298.1 2615.94
   336.4 2615.25     379 2615.37   387.1 2614.39   391.2 2612.56   395.3 2612.22
   400.6 2612.51   412.2 2613.53   431.7 2614.12   446.6 2613.85   464.3 2614.28
   476.5 2613.63   480.5 2613.69   496.8 2615.39   508.9 2615.83   521.8 2617.31
   532.2 2619.79   547.2 2624.53   557.7 2627.48   584.3 2633.37   610.4 2639.98
#Mann= 5 ,-1,0
       0     .05       0  384.69     .07       0   391.2    .045       0
   400.6     .07       0  591.32      .1       0
#XS Ineff= 2 , 0
          320.93 2620.67
Permanent Ineff=
       F       F
Bank Sta=391.2,400.6
XS Rating Curve= 0 ,0
Exp/Cntr(USF)=0,0
Exp/Cntr=0.3,0.1

Type RM Length L Ch R = 1 ,840     ,103.2,101.4,103.9
XS GIS Cut Line= 2
2270801.35454586469175.5584140632270302.78411244468907.447412504
#Sta/Elev= 30
       0 2628.61    10.4 2625.75    33.1 2621.98    58.7 2618.81    76.5 2617.62
   110.3 2616.67   185.7 2616.54   214.8 2616.04   233.1 2616.31   269.3 2615.34
   310.2 2612.39   337.4 2612.93     360 2612.43   368.9 2612.99   405.5 2611.14
   414.6 2611.33     425 2610.87   446.4    2612     451 2611.31   457.5 2609.06
   460.1 2608.55   473.7 2609.09   478.1 2609.68     487 2609.34   495.9 2612.95
   500.9 2614.27     510 2615.24   528.2 2616.22   541.8 2623.85   566.1 2635.23
#Mann= 5 ,-1,0
       0     .05       0     320     .07       0     360     .08       0
   457.5    .045       0   473.7     .08       0
#XS Ineff= 2 , 0
          369.14 2614.26
Permanent Ineff=
       F       F
Bank Sta=457.5,473.7
XS Rating Curve= 0 ,0
Exp/Cntr(USF)=0,0
Exp/Cntr=0.3,0.1

Type RM Length L Ch R = 1 ,739     ,181.8,182.6,184.5
XS GIS Cut Line= 2
2270865.79424115469131.2378753272270277.68583151468770.711647191
#Sta/Elev= 30
       0  2642.3    25.9 2632.36    34.7 2629.75    53.5 2622.79    72.8 2619.09
      91 2616.82   109.8 2615.98   148.1 2615.46   287.1 2615.08   349.1 2612.74
   398.3  2611.7   410.1 2610.84   424.4 2611.33   438.2 2610.39   471.1 2610.44
   478.5 2608.06   480.5 2607.48   485.2 2607.28   495.8    2608   516.7 2610.71
   536.8 2611.14   555.5  2614.6   583.7 2615.29   588.4  2617.9   600.9 2627.16
   607.1 2631.08   621.2 2638.01   654.1 2652.32   677.5 2663.66   689.8  2670.5
#Mann= 8 ,-1,0
       0     .05       0     290     .07       0     410     .08       0
     430     .07       0   478.5    .045       0   495.8     .07       0
     530     .08       0     620      .1       0
Bank Sta=478.5,495.8
XS Rating Curve= 0 ,0
Exp/Cntr(USF)=0,0
Exp/Cntr=0.3,0.1

Type RM Length L Ch R = 1 ,557     ,65.6,66.8,67.6
BEGIN DESCRIPTION:
structure xs 4
END DESCRIPTION:
XS GIS Cut Line= 5
2270897.26530056469045.692436171 2270666.4229987468910.249248857
2270545.11301354468730.0509213882270479.15807015468675.873646462
2270364.91468607468618.163070998
#Sta/Elev= 30
       0 2630.27    15.2 2624.83    47.6 2616.47    52.3 2615.97   121.8 2614.63
     210  2614.5   246.7 2614.38   268.9    2615   365.4 2611.91   399.1 2612.27
   408.8 2610.78   414.1 2611.44   437.2  2612.2   466.6 2610.15   494.7 2610.02
  511.182606.901   517.1  2606.5   525.9 2606.89     543 2607.84   553.4 2609.55
   565.7 2610.38   577.4 2613.36   582.5 2613.89   622.9 2615.02   629.4 2615.86
   634.3 2618.44   640.8 2624.35   645.3 2627.73   676.6  2645.8   698.2 2657.57
#Mann= 8 ,-1,0
       0     .05       0      80     .06       0     210     .05       0
  267.64     .06       0  357.64     .07       0  511.18    .045       0
   525.9     .07       0  640.22      .1       0
#XS Ineff= 2 , 0
          491.14 2613.33
Permanent Ineff=
       F       F
Bank Sta=511.18,525.9
XS Rating Curve= 0 ,0
Exp/Cntr(USF)=0,0
Exp/Cntr=0.5,0.3

Type RM Length L Ch R = 1 ,490     ,74.5,85.9,93.3
BEGIN DESCRIPTION:
structure xs 3; 13.2 ft between structure and xs
END DESCRIPTION:
XS GIS Cut Line= 6
2270927.75968661468988.1540285362270674.97108097 468845.94992818
2270616.08223192468779.7547050982270549.83323873468646.168997508
2270543.57392476468526.0581701692270437.66934524468452.997908646
#Sta/Elev= 30
       0 2622.03      13 2621.22    39.8 2617.57      89 2616.39   105.1 2614.94
   182.9 2613.95   242.7 2614.12   253.5 2614.85   292.3 2613.77     303  2612.6
   361.9 2614.18   425.2 2613.56   458.3 2609.47   493.9 2609.81   505.1 2606.22
   510.8 2605.39   522.7 2606.19   536.7 2607.31     545 2609.31   561.6 2611.42
   600.4 2610.68   648.1 2611.41   658.8 2612.11   669.2 2614.82   678.2 2615.31
   686.5 2618.39   698.4 2626.53   707.4 2630.23   746.2 2650.36   783.3 2665.63
#Mann= 6 ,-1,0
       0     .06       0  379.88     .07       0  459.88     .06       0
   505.1    .045       0   522.7     .06       0  684.64      .1       0
#XS Ineff= 2 ,-1
       0     492  2612.5     536783.2963  2613.8
Permanent Ineff=
       F       F
Bank Sta=505.1,522.7
XS Rating Curve= 0 ,0
Exp/Cntr(USF)=0,0
Exp/Cntr=0.5,0.3

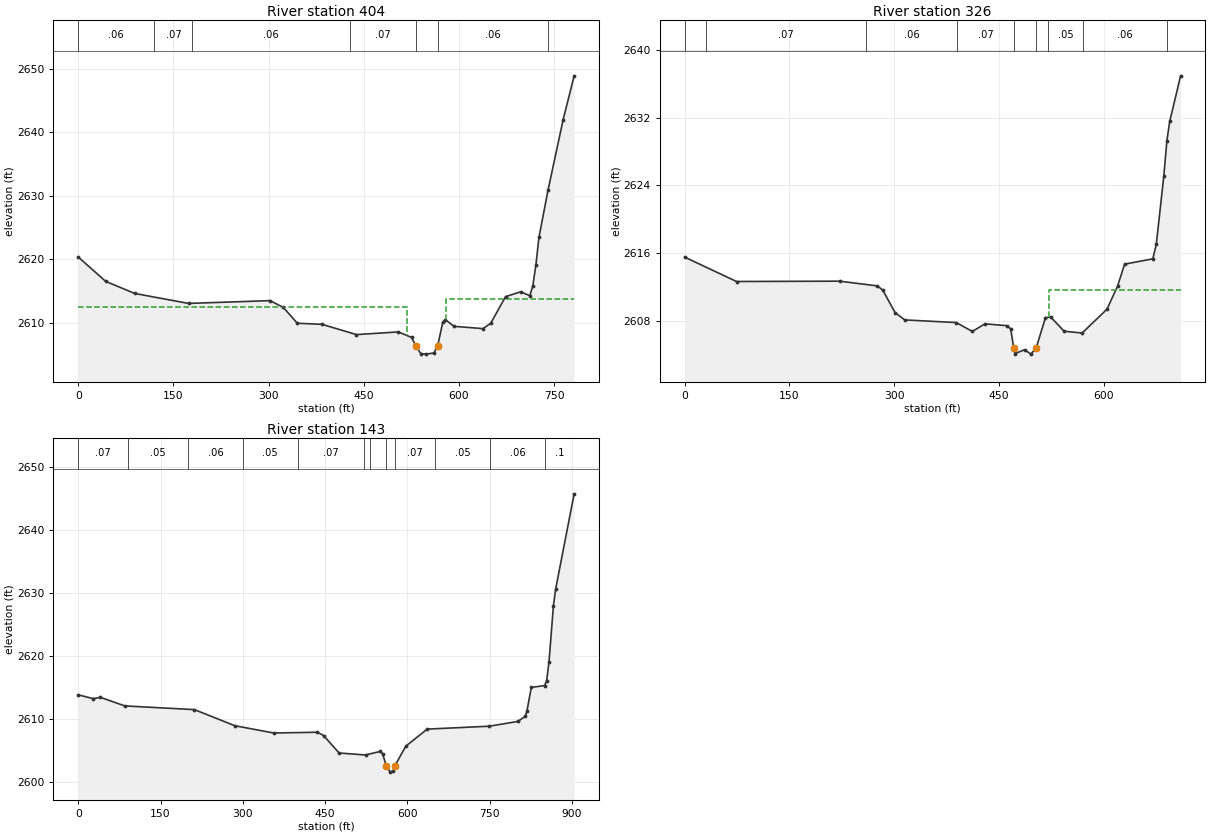
Type RM Length L Ch R = 1 ,404     ,88.8,78,72.2
BEGIN DESCRIPTION:
structure xs 2; 13.5 ft between structure and xs
END DESCRIPTION:
XS GIS Cut Line= 6
2270971.75965191468960.5153616742270768.80997428468859.106544224
2270718.97104627468818.311261318 2270646.9098059468726.968745715
2270591.76510547468497.2220131882270481.66931054468425.359241785
#Sta/Elev= 30
       0 2620.37    43.3 2616.54      89 2614.64   173.9 2613.07   302.3 2613.51
   323.3 2612.44   345.3 2609.96   384.4 2609.78   438.6 2608.17   504.5 2608.59
   525.4 2607.73   532.3 2606.37     540 2605.19     548  2605.1   560.5 2605.27
   566.4 2606.33   574.6 2610.11   578.6 2610.53   592.2 2609.47     638 2609.11
   650.2 2609.95   673.6 2614.14   697.5  2614.9   711.9 2614.28   716.6 2615.87
   721.4 2619.12   726.2 2623.44   740.5 2630.87   764.4 2641.98   781.7 2648.85
#Mann= 7 ,-1,0
       0     .06       0     120     .07       0     180     .06       0
  427.63     .07       0   532.3    .045       0   566.4     .06       0
  740.24      .1       0
#XS Ineff= 2 , 0
             519  2612.5     580          2613.8
Permanent Ineff=
       F       F
Bank Sta=532.3,566.4
XS Rating Curve= 0 ,0
Exp/Cntr(USF)=0,0
Exp/Cntr=0.5,0.3

Type RM Length L Ch R = 1 ,326     ,182.4,182.4,182.4
BEGIN DESCRIPTION:
structure xs 1
END DESCRIPTION:
XS GIS Cut Line= 4
 2270962.7491372468930.0357318742270712.59145907468578.118998227
 2270651.1120297468514.5195885322270500.59342675468398.980660919
#Sta/Elev= 30
       0 2615.51    74.2 2612.63   221.9 2612.67   275.9 2612.11   283.6 2611.61
   301.3 2608.95   315.1 2608.09   388.8 2607.78   411.8 2606.73   429.9 2607.63
     461 2607.41   466.7 2607.04  470.992604.789   472.7 2604.11   486.5 2604.57
   495.7 2604.05   503.32604.809   516.5 2608.36   523.9 2608.44   543.2 2606.76
   568.9 2606.54   604.6 2609.36   619.7 2612.08   629.8 2614.68   670.2 2615.31
   675.2 2617.03   685.9 2625.06   690.3 2629.22   694.4 2631.55     710 2636.93
#Mann= 9 ,-1,0
       0     .06       0      30     .07       0     260     .06       0
     390     .07       0  470.99    .045       0   503.3     .07       0
  520.23     .05       0  570.23     .06       0  690.23      .1       0
#XS Ineff= 2 , 0
                          521.46         2611.62
Permanent Ineff=
       F       F
Bank Sta=470.99,503.3
XS Rating Curve= 0 ,0
Exp/Cntr(USF)=0,0
Exp/Cntr=0.3,0.1

Type RM Length L Ch R = 1 ,143     ,,,
XS GIS Cut Line= 4
2270976.78147915468900.1808662542270890.23540244  468498.3597958
2270717.14324901468331.4495049962270466.77781281468363.904283764
#Sta/Elev= 30
       0 2613.85    27.6 2613.24    40.1 2613.46    84.9 2612.09   211.8  2611.5
   285.4 2608.94   356.5 2607.78   436.1  2607.9   447.2 2607.38   475.6  2604.6
   523.7 2604.29     551 2604.86   554.8 2604.48  561.532602.571   568.9 2601.56
   574.6  2601.8   577.4  2602.6   597.1 2605.68   636.2  2608.4   749.3 2608.86
   801.7 2609.63   814.6 2610.42   817.8 2611.22   825.9 2615.03   850.1 2615.32
   853.9 2616.12   858.2 2619.12   866.2 2628.01   870.3 2630.68     904 2645.81
#Mann= 12 ,-1,0
       0     .07       0      90     .05       0     200     .06       0
     300     .05       0     400     .07       0  521.04     .05       0
  531.04     .07       0  561.53    .045       0   577.4     .07       0
  651.04     .05       0  751.49     .06       0  851.49      .1       0
Bank Sta=561.53,577.4
XS Rating Curve= 0 ,0
Exp/Cntr(USF)=0,0
Exp/Cntr=0.3,0.1
LCMann Table=0

Chan Stop Cuts=-1
Use User Specified Reach Order=0
Composite Channel Slope=5